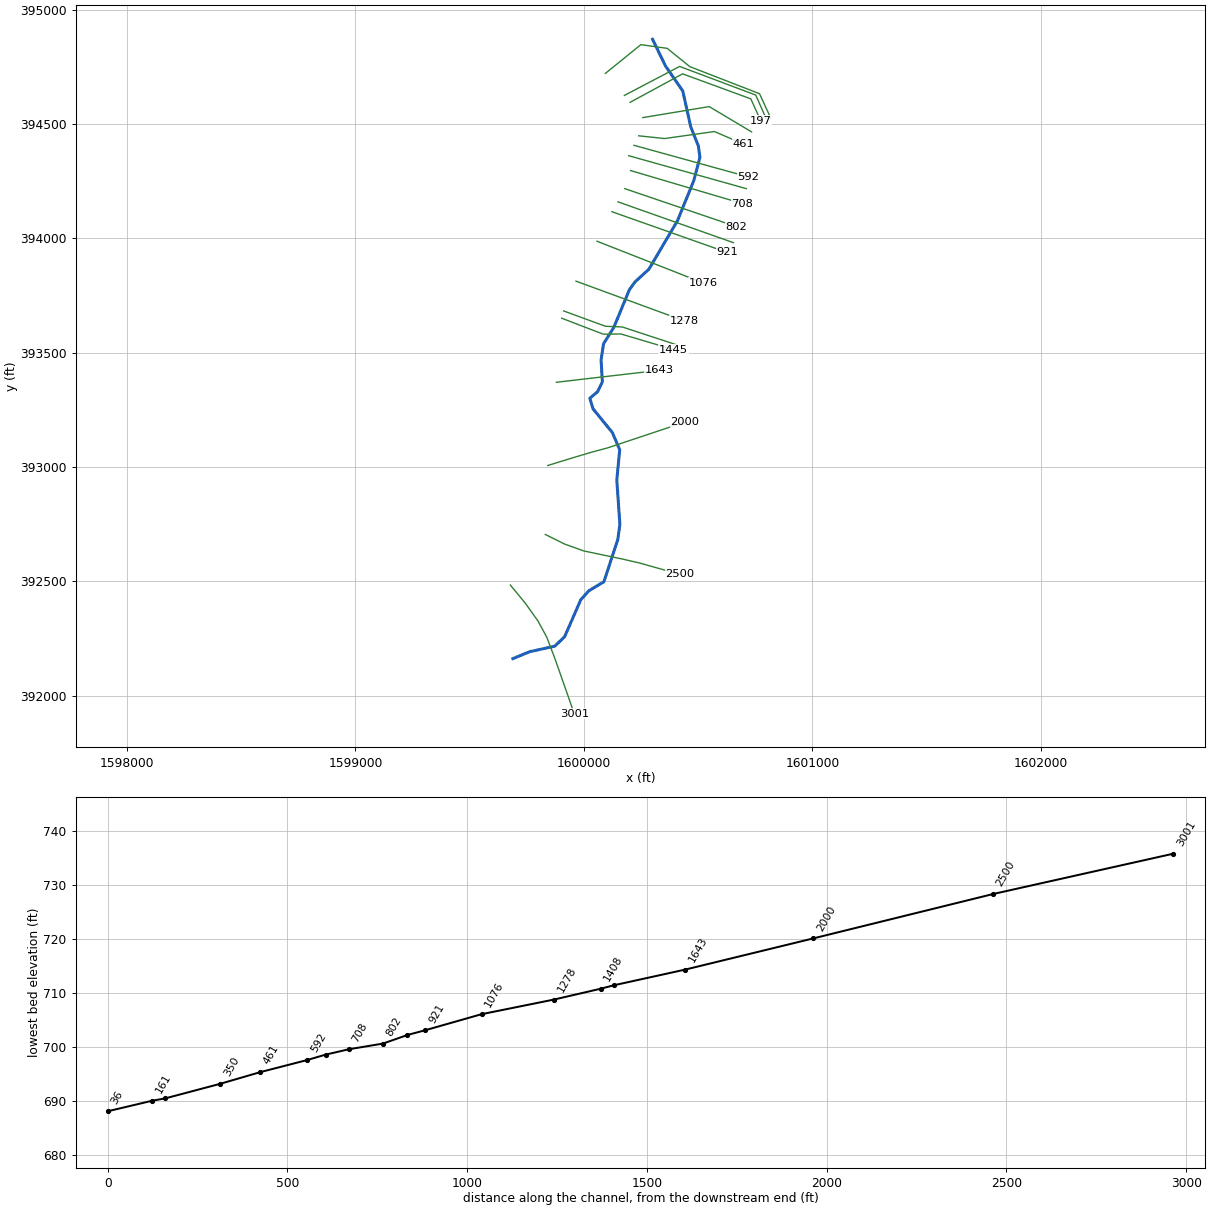
--- FLHRTYRN.prj (project) ---

Proj Title=FLHRTYRN
Current Plan=p01
Default Exp/Contr=0,0
English Units
Geom File=g01
Flow File=f01
Plan File=p01
BEGIN DESCRIPTION:
---------- MODELED AS PART OF WVEMD CTP PROGRAM, 2023----------
Stream Name:Fluharty Run
Flood Zone:  AFH
Wetzel County, WV
HEC-RAS Version: RAS 6.3
Vertical Datum: NAVD88
Projection: NAD 1983 StatePlane West Virginia S FIPS 4702 (US Feet)
Terrain: 1-meter West Virginia FEMA R3 South Central (collected 2018-2020)
Land Use: 2019 NLCD
Hydrologic Method:
WV SIR2010-5033 regression equations
Additional Model Notes:
Leveraged XS
END DESCRIPTION:
DSS File=dss
DSS Export Rating Curves= 0
DSS Export Rating Curve Sorted= 0
DSS Export Volume Flow Curves= 0
DXF OffsetX= 0
DXF OffsetY= 0
DXF ScaleX= 0
DXF ScaleY= 0

--- FLHRTYRN.p01 (plan) ---

Plan Title=Floodplain
Program Version=6.31
Short Identifier=Floodplain
Geom File=g01
Subcritical Flow
K Sum by GR= 0
Std Step Tol= 0.01
Critical Tol= 0.01
Num of Std Step Trials= 20
Max Error Tol= 0.3
Flow Tol Ratio= 0.001
Split Flow NTrial= 30
Split Flow Tol= 0.02
Split Flow Ratio= 0.02
Log Output Level= 0
Friction Slope Method= 1
Unsteady Friction Slope Method= 2
Unsteady Bridges Friction Slope Method= 1
Parabolic Critical Depth
Global Vel Dist= 0 , 0 , 0
Global Log Level= 0
CheckData=True
Encroach Param=-1 ,0,0, 0
Computation Interval=0.1SEC
Output Interval=1SEC
Instantaneous Interval=Max Profile
Mapping Interval=1HOUR
Computation Time Step Use Courant=        0
Computation Time Step Use Time Series=    0
Computation Time Step Count To Double=0
Computation Time Step Max Doubling=0
Computation Time Step Max Halving=0
Computation Time Step Residence Courant=0
Run HTab= 0
Run UNet= 0
Run Sediment= 0
Run PostProcess= 0
Run WQNet= 0
Run RASMapper= 0
UNET Theta= 0
UNET Theta Warmup= 0
UNET ZTol= 0
UNET ZSATol= 0
UNET MxIter= 0
UNET Max Iter WO Improvement= 0
UNET MaxInSteps= 0
UNET DtIC= 0
UNET DtMin= 0
UNET MaxCRTS= 0
UNET WFStab= 0
UNET SFStab= 0
UNET WFX= 1
UNET SFX= 1
UNET Gravity=32.17405
UNET 1D Methodology=Finite Difference
UNET DSS MLevel= 1
UNET Pardiso=0
UNET DZMax Abort= 0
UNET Use Existing IB Tables= 0
UNET Froude Reduction=False
UNET Froude Limit= 0
UNET Froude Power= 0
UNET D1 Cores= 0
UNET WindReference=Eulerian
UNET WindDragFormulation=Hsu (1988)
UNET D2 Coriolis=0
UNET D2 Cores= 0
UNET D2 Theta= 1
UNET D2 Theta Warmup= 1
UNET D2 Z Tol= 0.01
UNET D2 Volume Tol= 0.01
UNET D2 Max Iterations= 20
UNET D2 Equation= 0
UNET D2 RampUpFraction=0.1
UNET D2 TimeSlices= 1
UNET D2 Turbulence Formulation=Non-Conservative (original)
UNET D2 Eddy Viscosity=0.3
UNET D2 Transverse Eddy Viscosity=0.1
UNET D2 Smagorinsky Mixing=0
UNET D2 BCVolumeCheck=0
UNET D2 Cores=0
UNET D2 SolverType=PARDISO (Direct)
UNET D2 Minimum Iterations= 3
UNET D2 Maximum Iterations= 30
UNET D2 Restart Number= 10
UNET D2 Relaxation Coeff=1.3
UNET D2 SOR Precondition Iterations= 10
UNET D2 ILUT Maximum Fill= 8
UNET D2 ILUT Tolerance=1E-08
UNET D2 Convergence Tolerance=0.00001
UNET D1D2 MaxIter= 0
UNET D1D2 ZTol=0.01
UNET D1D2 QTol=0.1
UNET D1D2 MinQTol=1
DSS File=dss
Write IC File= 0
Write IC File at Fixed DateTime=0
Write IC File at Sim End=0
Echo Input=False
Echo Parameters=False
Echo Output=False
Write Detailed= 0
HDF Write Warmup=0
HDF Write Time Slices=0
HDF Flush=0
HDF Compression= 1
HDF Chunk Size= 1
HDF Spatial Parts= 1
HDF Use Max Rows=0
HDF Fixed Rows= 1
Calibration Method= 0
Calibration Iterations= 20
Calibration Max Change=0.05
Calibration Tolerance=0.2
Calibration Maximum=1.5
Calibration Minimum=0.5
Calibration Optimization Method= 1
WQ AD Non Conservative
WQ ULTIMATE=-1
WQ Max Comp Step=1HOUR
WQ Output Interval=15MIN
WQ Output Selected Increments= 0
WQ Create Restart=0
WQ Fixed Restart=0
WQ System Summary=0
WQ Write To DSS=0
Sorting and Armoring Iterations= 10
XS Update Threshold= 0.02
Bed Roughness Predictor= 0
Hydraulics Update Threshold= 0.02
Energy Slope Method= 1
Volume Change Method= 1
Sediment Retention Method= 0
Sediment TS Multiplier= 1
Warm Up Method= 0
XS Weighting Method= 0
Number of US Weighted Cross Sections= 1
Number of DS Weighted Cross Sections= 1
Upstream XS Weight=0
Main XS Weight=1
Downstream XS Weight=0
Number of DS XS's Weighted with US Boundary= 1
Upstream Boundary Weight= 1
Weight of XSs Associated with US Boundary= 0
Number of US XS's Weighted with DS Boundary= 1
Downstream Boundary Weight= 0.5
Weight of XSs Associated with DS Boundary= 0.5
Percentile Method= 0
Sediment Output Level= 3
Mass or Volume Output= 0
Output Increment Type= 1
Profile and TS Output Increment= 1
Transport Output Increment 1
XS Output Flag= 0
XS Output Increment= 10
Read HDF5 Sediment Hotstart= 0
Sediment Hotstart Type= 0
Write Gradation File= 0
Read Gradation Hotstart= 0
Write HDF5 File= 1
Write Binary Output= 1
Write DSS Sediment File= 0
DSS Sediment Output Type= 1
SV Curve= 0
Specific Gage Flag= 0
Subcell Erosion Methods= 0
Subcell Deposition Methods= 0
Advection Scheme= 1
Matrix Solver= 0
Implicit Weighting Factor= 1
Maximum Outer Loop Convergence Iterations= 5
Convergence Maximum Absolute= 0.001
Convergence RMSE= 0.0001
Grain Fractions Max Abs Error= 0.001
Max Subgrid Regions= 1
Max Subgrid Length Scale= 3.402823E+38
Initial Layer Thickness= 3.402823E+38
Min Layer Thickness= 3.402823E+38
Max Layer Thickness= 3.402823E+38
Number of Layers= 5

--- FLHRTYRN.f01 (steady flow) ---

Flow Title=Flow
Program Version=4.00
Number of Profiles=1
Profile Names=F01pct
River Rch & RM=FLHRTYRN,Main,3001
     686
River Rch & RM=FLHRTYRN,Main,2000
     767
Boundary for River Rch & Prof#=FLHRTYRN,Main      ,1
Up Type=0
Dn Type=3
Dn Slope=0.017153

--- FLHRTYRN.g01 (geometry) ---

Geom Title=Geometry
Program Version=6.31

River Reach=FLHRTYRN        ,Main
Reach XY= 30
     1599688.872      392161.631      1599762.91       392191.92
     1599872.847      392216.225     1599915.849      392258.106
     1599986.522      392419.645     1600022.046      392458.534
     1600087.484      392497.797     1600148.435      392682.893
     1600157.409      392748.706     1600143.948      392942.403
     1600156.661      393074.775     1600124.503      393150.309
     1600039.994      393253.889     1600025.785      393299.883
     1600060.187      393329.423     1600080.753      393372.425
     1600075.144      393467.778     1600085.988      393538.826
     1600130.486      393609.499     1600198.916      393774.403
     1600223.595      393809.179     1600284.173      393864.147
      1600409.44      394076.541     1600481.235      394253.037
     1600507.784      394353.999     1600501.053      394402.984
       1600467.4      394488.241     1600432.624      394644.171
     1600357.464      394752.611     1600300.334        394870.4

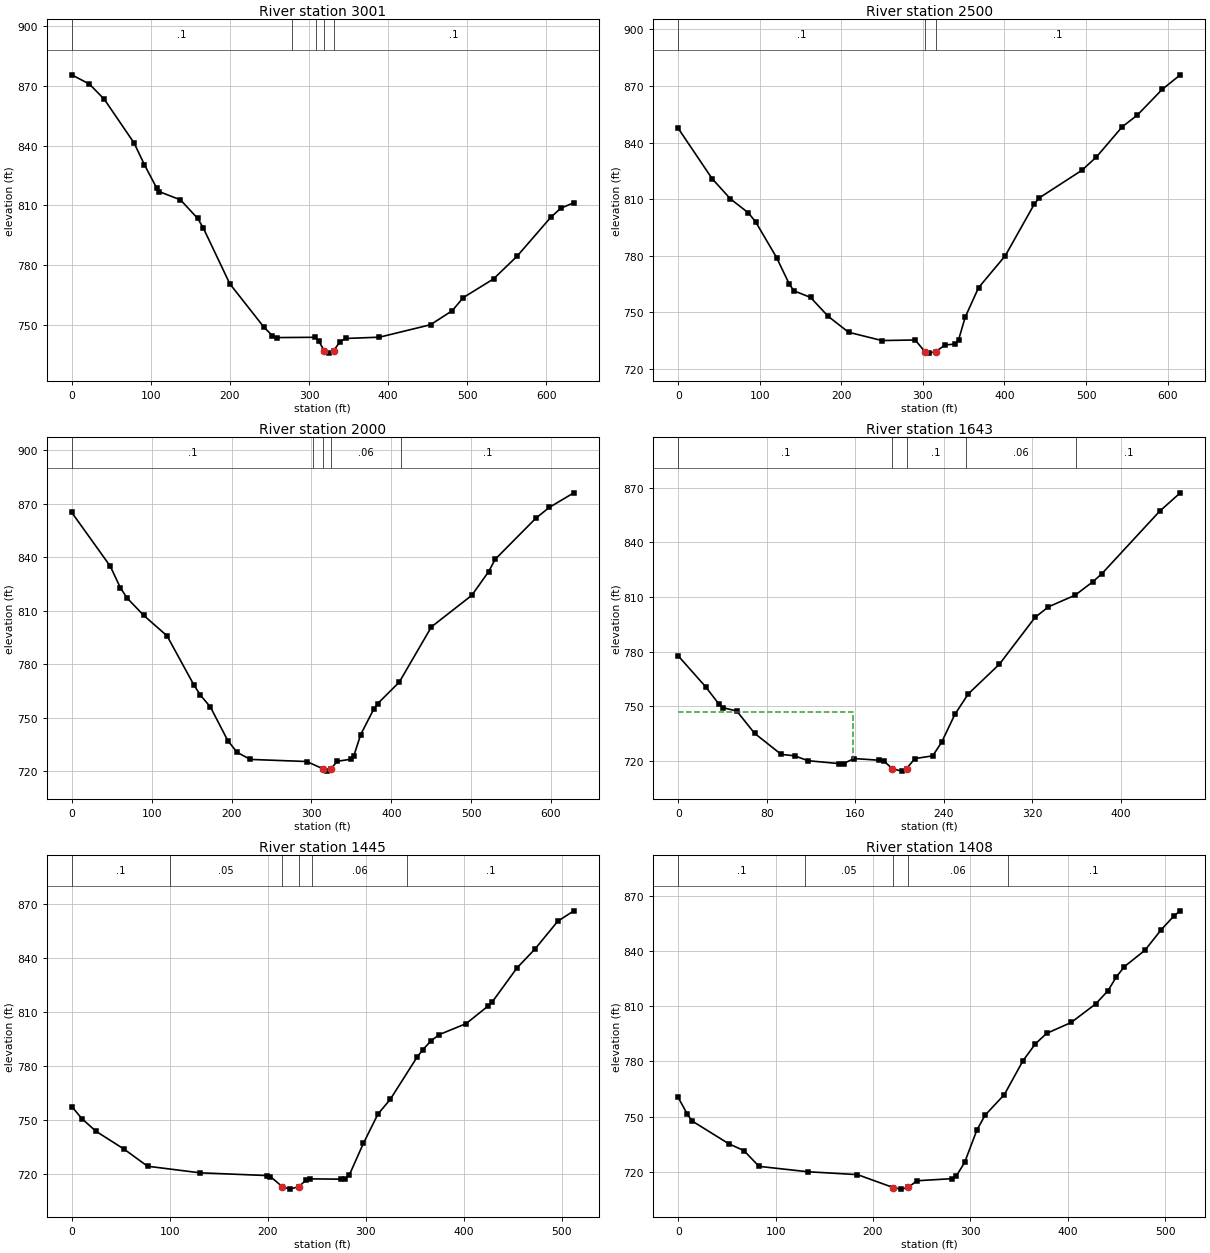
Type RM Length L Ch R = 1 ,3001    ,491.9,501.2,504.7
XS GIS Cut Line= 6
1599677.89434434392483.3603444991599743.69506575392403.878548086
1599799.40033492 392325.422340171599837.06725433392256.063883096
1599872.79881017 392162.514857591599957.74286601391920.753530085
#Sta/Elev= 30
       0  875.59    22.3  870.94    41.1  863.32    78.8  841.33    91.9   830.4
   107.3  818.75   110.8  816.89   137.4   812.8   159.2  803.46   166.1  798.81
   199.8  770.64   242.8   748.9   253.7  744.55   259.6  743.63   307.8  743.77
   312.1  741.92   319.3  737.03   324.9  735.82   330.9  736.97   339.2  741.61
   346.3  743.18     389  743.83   453.5  750.08   480.9  757.11     495  763.73
   533.2   773.1   562.9  784.48   605.4  803.97     618  808.54   634.7  811.38
#Mann= 5 ,-1,0
       0      .1       0  278.33     .06       0  308.33      .1       0
   319.3    .045       0   330.9      .1       0
Bank Sta=319.3,330.9
XS Rating Curve= 0 ,0
Exp/Cntr(USF)=0,0
Exp/Cntr=0.3,0.1

Type RM Length L Ch R = 1 ,2500    ,496.1,500,502.2
XS GIS Cut Line= 6
1599830.94784401392704.6525528431599916.76755425 392662.11425209
1599999.94619368392632.4558468461600171.22373825392596.514645755
1600244.29609868392579.5822649151600419.01425317392530.421602085
#Sta/Elev= 30
       0  847.53    41.5  820.92    63.8  810.22    86.1  802.69    95.1  797.81
   120.6  779.01   136.2  764.93   141.8   761.4   162.2  757.89   183.8  747.88
   208.8  739.42   249.7  735.01   290.5  735.31   302.4  729.15   306.9  728.34
   315.9   729.2   327.3   732.7   339.6  733.12   343.7  735.34   351.8  747.36
   368.2  763.04   401.1  780.07   436.4  807.24   442.2  810.54     495  825.33
   512.8   832.4   544.4  848.39   562.7   854.5   593.4  868.21   615.6  875.94
#Mann= 3 ,-1,0
       0      .1       0   302.4    .045       0   315.9      .1       0
Bank Sta=302.4,315.9
XS Rating Curve= 0 ,0
Exp/Cntr(USF)=0,0
Exp/Cntr=0.3,0.1

Type RM Length L Ch R = 1 ,2000    ,357.5,357.1,355.6
XS GIS Cut Line= 6
1599842.07150942393006.3081175091599938.80884875393036.103989676
1600028.95860285393063.1311665921600103.30687934393083.082242176
1600198.17512792393114.7052104181600441.27470735393195.739825249
#Sta/Elev= 30
       0  865.23    48.2  835.07    60.7  823.12    69.1  817.28      90  807.53
   119.3  795.99   152.7  768.61     161  762.77   173.6  756.07   195.3  737.26
   206.9  730.69   223.5  726.68   294.2   725.5  314.57 721.399   319.5  720.11
   324.7  721.46   332.2  725.62   349.1  726.77   353.2  728.78   361.7  740.59
   378.1  754.91   382.8  757.89   410.1  770.09   450.3  801.06   500.9  818.77
   521.9  832.03   530.2     839   580.8   861.9   597.8  868.06   628.6  876.25
#Mann= 5 ,-1,0
       0      .1       0  302.31     .06       0  314.57    .045       0
   324.7     .06       0  412.31      .1       0
Bank Sta=314.57,324.7
XS Rating Curve= 0 ,0
Exp/Cntr(USF)=0,0
Exp/Cntr=0.3,0.1

Type RM Length L Ch R = 1 ,1643    ,197.8,197.9,197.8
BEGIN DESCRIPTION:
Structure 4 XS 4
END DESCRIPTION:
XS GIS Cut Line= 2
 1599879.5938379393370.2303549821600330.61957743393422.537497641
#Sta/Elev= 30
       0  777.65    24.7  760.72    36.8  751.15    40.8  749.11    52.9  747.36
      69  735.11    93.1  723.51   105.2  722.74   117.3  720.04   145.5  718.44
   149.5  718.46   158.9  721.23   181.7   720.3   185.8   719.9  193.59  715.67
   201.9  714.31  206.53715.6691   213.9   721.2   230.1   722.7   238.1  730.12
   250.2  745.55   262.3  756.77   290.5  773.14   322.7  798.84   334.7  804.59
   358.9  811.02     375  818.43   383.1  822.83   435.4  857.21     454  867.27
#Mann= 5 ,-1,0
       0      .1       0  193.59    .045       0  206.53      .1       0
     260     .06       0     360      .1       0
#XS Ineff= 2 , 0
           157.8  746.55
Permanent Ineff=
       F       F
Bank Sta=193.59,206.53
XS Rating Curve= 0 ,0
Exp/Cntr(USF)=0,0
Exp/Cntr=0.3,0.1

Type RM Length L Ch R = 1 ,1445    ,37,37.2,35.4
BEGIN DESCRIPTION:
Structure 4 XS 3
END DESCRIPTION:
XS GIS Cut Line= 4
1599902.29316396393650.5176854541600084.87469965393580.445852836
1600161.85502281393581.4327800561600391.80906506393513.334801878
#Sta/Elev= 30
       0   757.3    10.5  750.49    24.6   743.6    53.4  733.63    77.3  724.14
   130.5  720.49   198.8  718.96   202.8  718.37   214.7  712.82   222.8  711.41
  231.79712.8282   238.8   716.3   242.8  717.11   275.1  716.94   279.1  717.21
   283.3  719.33   297.6  736.82   312.5  753.15     325  761.26   352.3  784.67
   358.3  788.91   366.7  793.84     375  797.27   402.5   803.4   425.1  813.26
   429.3  815.57   454.3  834.29   472.9  844.94     496  860.29   512.4  866.07
#Mann= 6 ,-1,0
       0      .1       0     100     .05       0   214.7    .045       0
  231.79     .05       0  245.57     .06       0  342.55      .1       0
Bank Sta=214.7,231.79
XS Rating Curve= 0 ,0
Exp/Cntr(USF)=0,0
Exp/Cntr=0.3,0.1

Type RM Length L Ch R = 1 ,1408    ,133.1,129.4,128.5
BEGIN DESCRIPTION:
Structure 4 XS 2
END DESCRIPTION:
XS GIS Cut Line= 4
1599911.17550894393682.0993564931600094.74397185393614.988305535
1600167.77658613393612.0275238751600402.66526448393535.047200717
#Sta/Elev= 30
       0  760.46     9.5  751.26    14.4  747.67    52.1  735.31    67.4  731.67
      83   723.1     133  720.19   184.1  718.62   220.8  711.62   228.8  710.76
     236  711.66   245.3   715.3   281.5  716.45   285.7  717.93   294.2  725.28
   306.8  742.84   315.2  750.88     335  762.06     354  780.31   366.7  789.47
   378.3  795.21   403.6  801.14   428.9  811.26   441.5  818.44   449.9  825.81
   458.3  831.45   479.4  840.32   496.2  851.53   509.4  859.06   515.7   861.7
#Mann= 5 ,-1,0
       0      .1       0     130     .05       0   220.8    .045       0
     236     .06       0  338.54      .1       0
Bank Sta=220.8,236
XS Rating Curve= 0 ,0
Exp/Cntr(USF)=0,0
Exp/Cntr=0.3,0.1

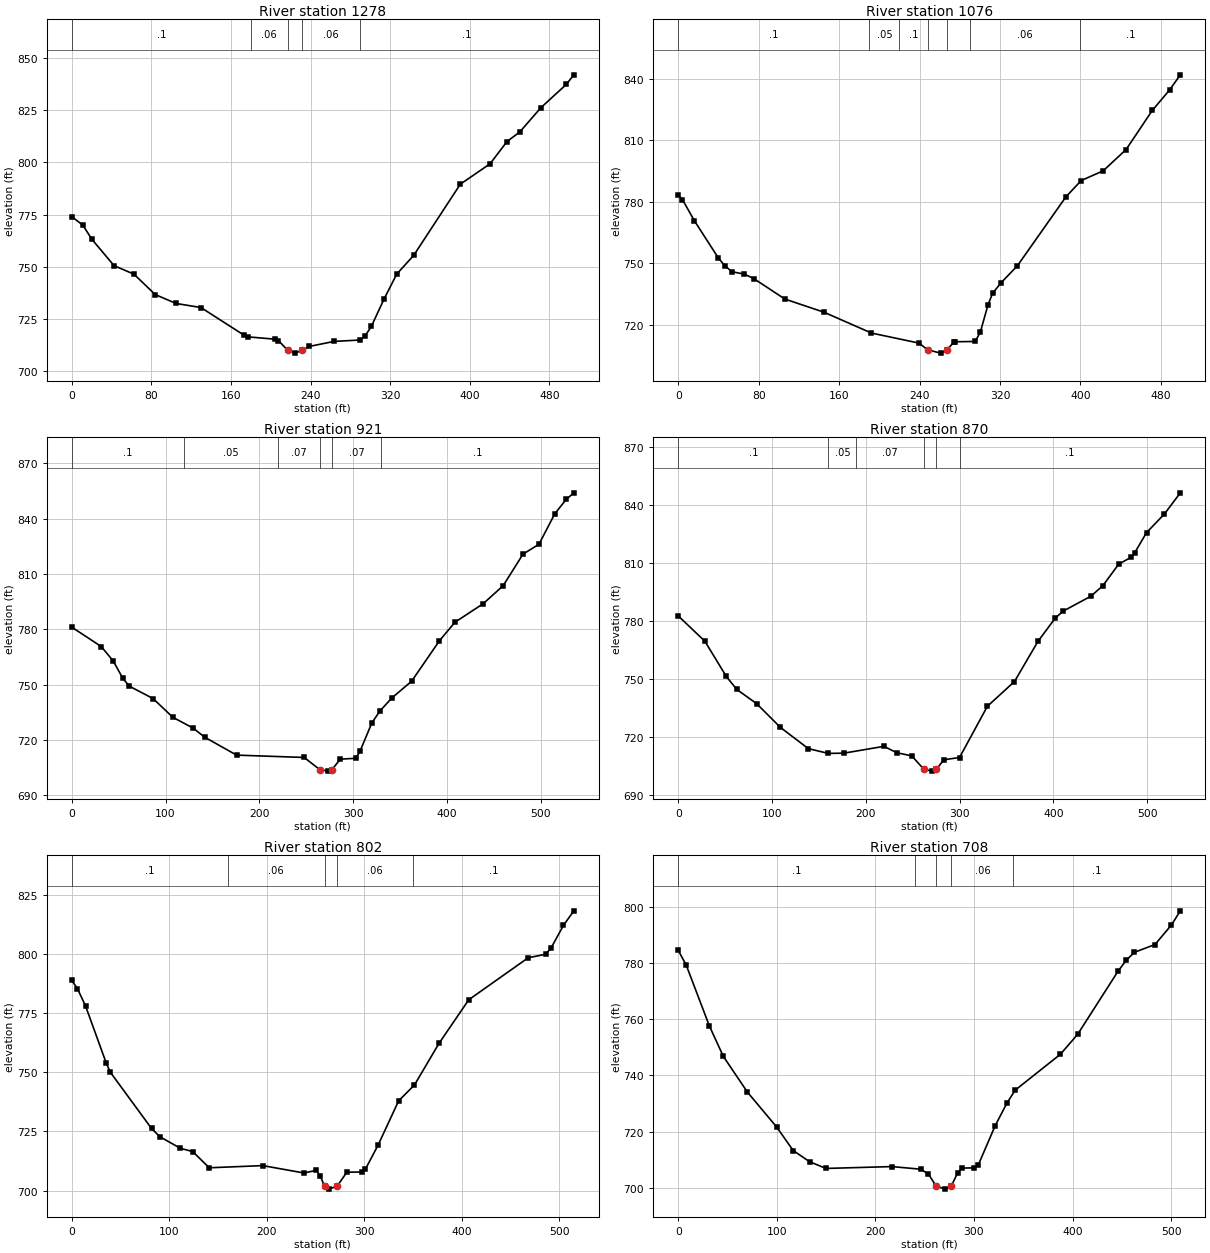
Type RM Length L Ch R = 1 ,1278    ,200.5,201.7,201.9
BEGIN DESCRIPTION:
Structure 4 XS 1
END DESCRIPTION:
XS GIS Cut Line= 2
1599965.45650604393812.3737495291600439.18157162393638.674558814
#Sta/Elev= 30
       0  774.07    11.3  769.92    19.9  763.41    42.5   750.6    62.5  746.54
    83.8   736.8   104.8  732.52   129.8  730.58   173.4  717.27   177.5  716.52
   204.6  715.42   207.7  714.78     217  710.11   224.4  708.76   231.6 710.095
   238.9  711.98   263.8  714.38     290  715.03     295  717.13   301.1  721.57
   313.8  734.59   326.6  746.57   343.7  755.56   390.5  789.59   420.4  799.35
   437.4  809.99   450.2  814.56   471.5   826.2     497  837.34   504.6  841.92
#Mann= 5 ,-1,0
       0      .1       0     180     .06       0     217    .045       0
   231.6     .06       0     290      .1       0
Bank Sta=217,231.6
XS Rating Curve= 0 ,0
Exp/Cntr(USF)=0,0
Exp/Cntr=0.3,0.1

Type RM Length L Ch R = 1 ,1076    ,156.5,155.9,155.7
BEGIN DESCRIPTION:
Structure 3 XS 4
END DESCRIPTION:
XS GIS Cut Line= 2
1600057.24073749393987.059867464 1600522.0834581393804.478331769
#Sta/Elev= 30
       0  783.39     4.2  781.05      16  770.79    39.7   752.7    46.1  748.82
    53.5  745.82    65.9  744.63    75.1  742.48   106.2  732.43   144.9  726.05
   192.2  715.85   239.4  710.95     248   707.7   260.9  706.04  267.36707.6326
   273.8  711.24   275.7  711.59   295.3  711.75   300.4  716.15   308.2  729.77
   312.7   735.3   321.1  740.41   337.4  748.75   385.6   782.4   400.8  790.37
   422.7  795.14   445.4   805.5   471.5  824.62     489  834.81   499.4  842.04
#Mann= 7 ,-1,0
       0      .1       0     190     .05       0     220      .1       0
     248    .045       0  267.36      .1       0     290     .06       0
     400      .1       0
Bank Sta=248,267.36
XS Rating Curve= 0 ,0
Exp/Cntr(USF)=0,0
Exp/Cntr=0.3,0.1

Type RM Length L Ch R = 1 ,921     ,50.2,50.4,50.3
BEGIN DESCRIPTION:
Structure 3 XS 3
END DESCRIPTION:
XS GIS Cut Line= 2
1600122.47079366394116.0762121441600627.24604359393937.803586287
#Sta/Elev= 30
       0  781.13    31.4  770.66    44.2   762.8    54.2  753.61    61.1  749.22
    86.6  742.46   107.8  732.25   129.5  726.38   141.7  721.49   175.7  711.76
   247.8  710.49   264.3  703.95   273.2  703.08   277.5  703.94   286.2  709.57
   302.9  710.05   307.2  713.73   319.9  729.19   328.4  735.57   341.1  742.69
   362.3  751.81     392  773.78   408.5   783.8   438.7  793.89   459.9  803.61
   481.1  820.75   498.1   826.1     515  842.64   527.1  850.39   535.3  853.99
#Mann= 6 ,-1,0
       0      .1       0     120     .05       0     220     .07       0
   264.3    .045       0   277.5     .07       0     330      .1       0
Bank Sta=264.3,277.5
XS Rating Curve= 0 ,0
Exp/Cntr(USF)=0,0
Exp/Cntr=0.3,0.1

Type RM Length L Ch R = 1 ,870     ,67.7,67.9,67.8
BEGIN DESCRIPTION:
Structure 3 XS 2
END DESCRIPTION:
XS GIS Cut Line= 2
 1600149.2907123 394159.098066871600654.06596223393980.825441013
#Sta/Elev= 30
       0  782.58    28.4  769.46    51.2  751.25    62.4   744.5    83.6  737.12
     109   724.8   138.7  713.83     160  711.36   176.6  711.49   219.3  715.01
   233.1   711.7     249  710.08   261.8  703.18   270.2  702.18  275.29703.1845
   283.2  708.08   299.9  709.22   329.6  735.76   358.5   748.6   383.5  769.36
   401.8  781.34   410.2  785.01     440  792.79   452.7  798.22   469.6  809.36
   482.4  812.85   486.6  815.21   499.3  825.73   518.4  835.39   535.3  846.33
#Mann= 6 ,-1,0
       0      .1       0     160     .05       0     190     .07       0
   261.8    .045       0  275.29     .07       0     300      .1       0
Bank Sta=261.8,275.29
XS Rating Curve= 0 ,0
Exp/Cntr(USF)=0,0
Exp/Cntr=0.3,0.1

Type RM Length L Ch R = 1 ,802     ,94,94.6,94.8
BEGIN DESCRIPTION:
Structure 3 XS 1
END DESCRIPTION:
XS GIS Cut Line= 2
1600178.63278555394217.0139097171600666.17483222394051.210136762
#Sta/Elev= 30
       0  788.88     5.8  785.42    14.2  778.02    35.4  753.87    39.6  750.02
    81.8  726.26    90.3  722.77   111.4  717.87   124.1  716.47     141  709.62
   195.9  710.54   238.2  707.42   250.8  708.53   255.1  705.98   259.3   701.8
   263.5  700.59  272.27701.8427   282.1  707.75   297.3  707.83   301.1  708.94
   314.2  719.21   335.3  737.96   351.5  744.65   376.7  762.26   407.2   780.7
   468.2  798.48     486  799.94   491.7  802.64   504.3  812.16     515  818.33
#Mann= 5 ,-1,0
       0      .1       0     160     .06       0   259.3    .045       0
  272.27     .06       0     350      .1       0
Bank Sta=259.3,272.27
XS Rating Curve= 0 ,0
Exp/Cntr(USF)=0,0
Exp/Cntr=0.3,0.1

Type RM Length L Ch R = 1 ,708     ,64.7,64.9,64.8
BEGIN DESCRIPTION:
Structure 2 XS 4
END DESCRIPTION:
XS GIS Cut Line= 2
1600204.29289327394295.9680873141600692.82186715394151.876713199
#Sta/Elev= 30
       0   784.5     8.2  779.15    31.6  757.58    45.7  746.79    70.2  734.05
    99.9  721.61   116.6  713.27   133.3  709.28   149.9   706.9   216.7  707.56
   245.9  706.63   253.8   704.9  261.66700.5895   270.9  699.54  276.92700.5784
   283.4  705.31   287.6  707.02   300.1  707.11   304.3  708.08   321.4  722.02
   333.4  730.15   341.8  734.75   387.7  747.53   405.2  754.63     446     777
   454.4  780.94   462.7  783.78   483.6  786.56   500.3  793.51   509.3  798.55
#Mann= 5 ,-1,0
       0      .1       0     240     .06       0  261.66    .045       0
  276.92     .06       0     340      .1       0
Bank Sta=261.66,276.92
XS Rating Curve= 0 ,0
Exp/Cntr(USF)=0,0
Exp/Cntr=0.3,0.1

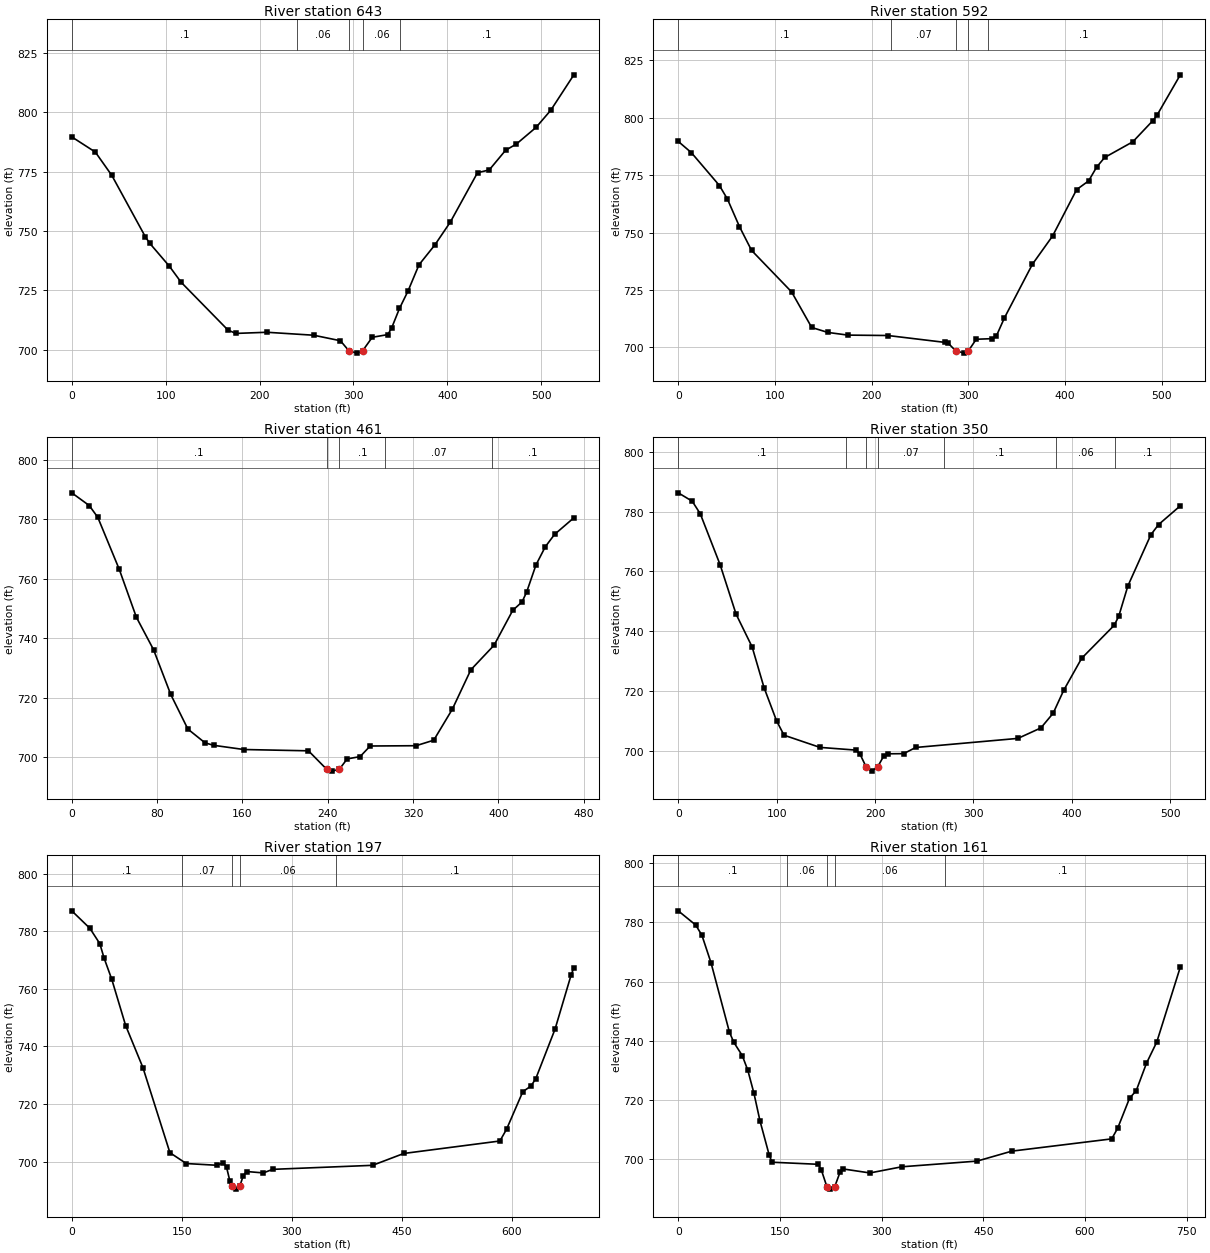
Type RM Length L Ch R = 1 ,643     ,51.1,51.1,51.1
BEGIN DESCRIPTION:
Structure 2 XS 3
END DESCRIPTION:
XS GIS Cut Line= 2
1600195.96918794394360.9683082591600710.91269577394216.966314695
#Sta/Elev= 30
       0  789.65    25.1  783.25    42.7  773.39    78.4  747.53    83.2  744.74
     104  735.13   116.4  728.43   166.3  708.28   174.6  706.84   207.8  707.33
   257.7  706.08   286.1  703.76     295  699.58   303.4  698.54  309.72699.5117
     320  705.21   336.6  706.35   340.7  709.18     349  717.37   358.1  724.71
   369.8  735.77   386.7  744.13   403.2  753.79   432.1  774.56   444.6  775.73
     462  784.01   473.6  786.67   494.4  793.63   510.1  800.86   534.7   815.8
#Mann= 5 ,-1,0
       0      .1       0     240     .06       0     295    .045       0
  309.72     .06       0     350      .1       0
Bank Sta=295,309.72
XS Rating Curve= 0 ,0
Exp/Cntr(USF)=0,0
Exp/Cntr=0.3,0.1

Type RM Length L Ch R = 1 ,592     ,127,130.3,132.2
BEGIN DESCRIPTION:
Structure 2 XS 2
END DESCRIPTION:
XS GIS Cut Line= 2
1600219.09680157394406.5039359511600719.46890209394268.334125155
#Sta/Elev= 30
       0  789.64    13.5  784.78    42.6  770.44    50.9  764.52    63.3  752.57
    75.8  742.24   117.2  724.17     138   708.7   154.6  706.55   175.3  705.38
   216.8   705.2   275.6  702.22   279.1  701.86  286.89698.5326   295.7  697.54
   299.8  698.41   308.1  703.57   324.7  703.84   328.9  704.97   337.2  712.83
   366.2  736.22     387  748.47   411.9  768.67   424.3  772.46   432.6  778.46
   440.9  782.65     470  789.47   490.7  798.67   494.9  800.94   519.1   818.6
#Mann= 5 ,-1,0
       0      .1       0     220     .07       0  286.89    .045       0
   299.8     .07       0     320      .1       0
Bank Sta=286.89,299.8
XS Rating Curve= 0 ,0
Exp/Cntr(USF)=0,0
Exp/Cntr=0.3,0.1

Type RM Length L Ch R = 1 ,461     ,110.7,111.1,111.2
BEGIN DESCRIPTION:
Structure 2 XS 1
END DESCRIPTION:
XS GIS Cut Line= 4
1600239.82227319 394447.954879191600353.31890349 394436.11175255
 1600571.4298191394466.7064963691600696.76957603394412.425499271
#Sta/Elev= 30
       0  788.91    16.4  784.63    24.4  780.67    44.5  763.21    60.6  747.06
    76.7  736.15    92.8  721.11   108.9  709.44     125  704.81   133.1  703.98
   161.4  702.57     222  702.13     239  695.95   244.5   695.3  251.09695.9887
   258.3  699.41   270.4  700.18   279.9  703.75   322.9  703.85   339.5   705.7
   356.9  716.11   374.3  729.39   396.1  737.66   413.6  749.38   422.3  752.21
   426.6   755.5   435.4  764.67   444.1  770.75   452.8  774.92   470.9   780.5
#Mann= 5 ,-1,0
       0      .1       0     239    .045       0  251.09      .1       0
  294.11     .07       0  394.36      .1       0
Bank Sta=239,251.09
XS Rating Curve= 0 ,0
Exp/Cntr(USF)=0,0
Exp/Cntr=0.3,0.1

Type RM Length L Ch R = 1 ,350     ,151.1,153.1,154.9
BEGIN DESCRIPTION:
Structure 1 XS 4
END DESCRIPTION:
XS GIS Cut Line= 3
  1600258.063649394527.697611636 1600548.4245456394575.744189486
 1600733.8523794394465.224131685
#Sta/Elev= 30
       0  786.32    14.2  783.52    22.4   779.3    42.6  762.21    58.8  745.68
    75.1  734.72    87.2   721.1    99.9     710   107.5  705.17     144  701.09
   180.5  700.18   184.5  698.97   190.9  694.58   196.7  693.14  202.77 694.627
   208.9  698.24   212.9  698.94   229.1  698.99   241.3  701.06   345.2   704.1
   368.5   707.6     381  712.53   391.7   720.2     410  730.94     443  741.96
   447.6  744.96   456.9  755.13   480.3   772.3   488.1  775.69   510.2  781.97
#Mann= 7 ,-1,0
       0      .1       0     170     .07       0   190.9    .045       0
  202.77     .07       0     270      .1       0  384.31     .06       0
  444.31      .1       0
Bank Sta=190.9,202.77
XS Rating Curve= 0 ,0
Exp/Cntr(USF)=0,0
Exp/Cntr=0.3,0.1

Type RM Length L Ch R = 1 ,197     ,36.2,36,36
BEGIN DESCRIPTION:
Structure 1 XS 3
END DESCRIPTION:
XS GIS Cut Line= 4
1600202.42365312394594.5175190641600431.93456505394718.985819265
1600730.51459154394609.6263878751600774.40225809394513.217415465
#Sta/Elev= 30
       0  787.11    24.7  781.04    38.3  775.69      44  770.76    54.6   763.3
    73.5  747.26    97.1  732.63   133.9  703.09   156.2  699.32   197.6  698.72
   206.7  699.57   211.2  698.01   215.8  693.15  218.31 691.615     224  690.43
   229.4  691.56     234  695.15   238.5  696.55   261.3  696.06   274.1   697.3
   410.4   698.7     453  702.82   584.1  707.15   593.2  711.23   615.4   724.3
   626.4  726.22     633  728.77   659.4  746.05   681.3  764.84     685  767.32
#Mann= 5 ,-1,0
       0      .1       0     150     .07       0  218.31    .045       0
   229.4     .06       0  361.09      .1       0
Bank Sta=218.31,229.4
XS Rating Curve= 0 ,0
Exp/Cntr(USF)=0,0
Exp/Cntr=0.3,0.1

Type RM Length L Ch R = 1 ,161     ,129.2,124.7,119.2
BEGIN DESCRIPTION:
Structure 1 XS 2
END DESCRIPTION:
XS GIS Cut Line= 4
 1600177.2422051394624.7352566851600418.98410607394751.361966716
1600752.09868984394626.1741965721600797.42529627394524.009464615
#Sta/Elev= 30
       0  783.93    25.8  779.13    34.9  775.69    48.4  766.36    75.5     743
      82  739.53    94.4  735.09   102.6  730.14   111.6   722.4   120.6     713
   134.2  701.47   138.3  699.08   206.4  698.38     211  696.52  219.17690.8561
   224.5     690  230.77690.8126     239  695.93   242.6  696.83   282.7  695.46
   329.7  697.54   440.8  699.46     492  702.82   639.3  706.96   648.1  710.55
   665.6  720.67   675.5  723.24   690.6  732.49   705.8  739.66   740.5  764.95
#Mann= 5 ,-1,0
       0      .1       0     160     .06       0  219.17    .045       0
  230.77     .06       0   392.9      .1       0
Bank Sta=219.17,230.77
XS Rating Curve= 0 ,0
Exp/Cntr(USF)=0,0
Exp/Cntr=0.3,0.1

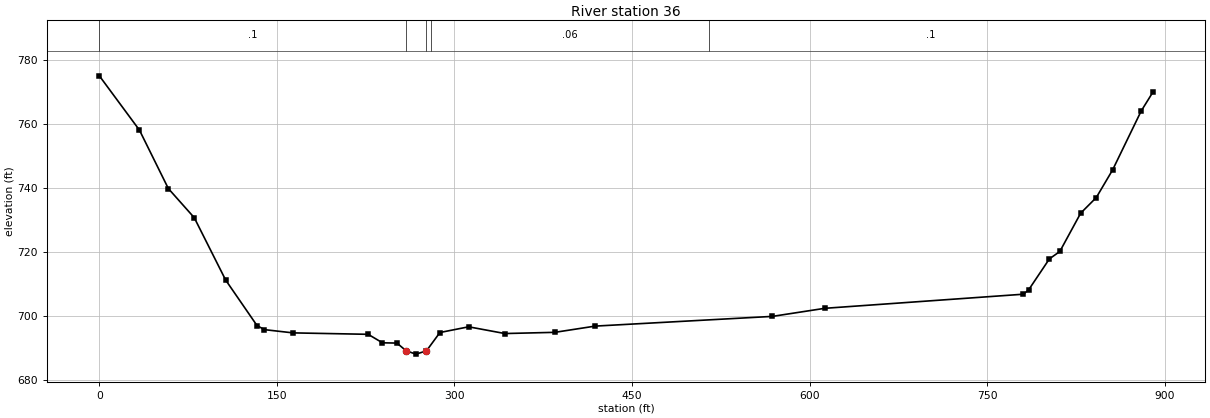
Type RM Length L Ch R = 1 ,36      ,,,
BEGIN DESCRIPTION:
Structure 1 XS 1
END DESCRIPTION:
XS GIS Cut Line= 6
1600093.79201844 394720.805085881600249.48012584394846.709381431
1600364.55394435394830.4636658761600463.38204731 394750.58889773
1600768.60333034394632.1961599981600817.81217061394525.229185764
#Sta/Elev= 30
       0  775.12    33.9  758.12    58.3  739.84    80.2  730.72   106.7  711.22
   133.2  696.97   139.5  695.69   163.6  694.68   227.1  694.23   239.2  691.57
   251.4  691.49  259.26  689.05   267.5  688.03  276.34689.0521   287.7  694.79
     312  696.58   342.6  694.47   384.8  694.85   418.9   696.8   568.6  699.84
   612.9  702.37   780.6  706.78     785  708.11   802.6  717.84   811.4  720.15
     829  732.13   842.2  737.03     856  745.68   880.1  764.09   889.9  769.94
#Mann= 5 ,-1,0
       0      .1       0  259.26    .045       0  276.34      .1       0
  280.23     .06       0  514.79      .1       0
Bank Sta=259.26,276.34
XS Rating Curve= 0 ,0
Exp/Cntr(USF)=0,0
Exp/Cntr=0.3,0.1
LCMann Table=0

Chan Stop Cuts=-1
Use User Specified Reach Order=0
Composite Channel Slope=5